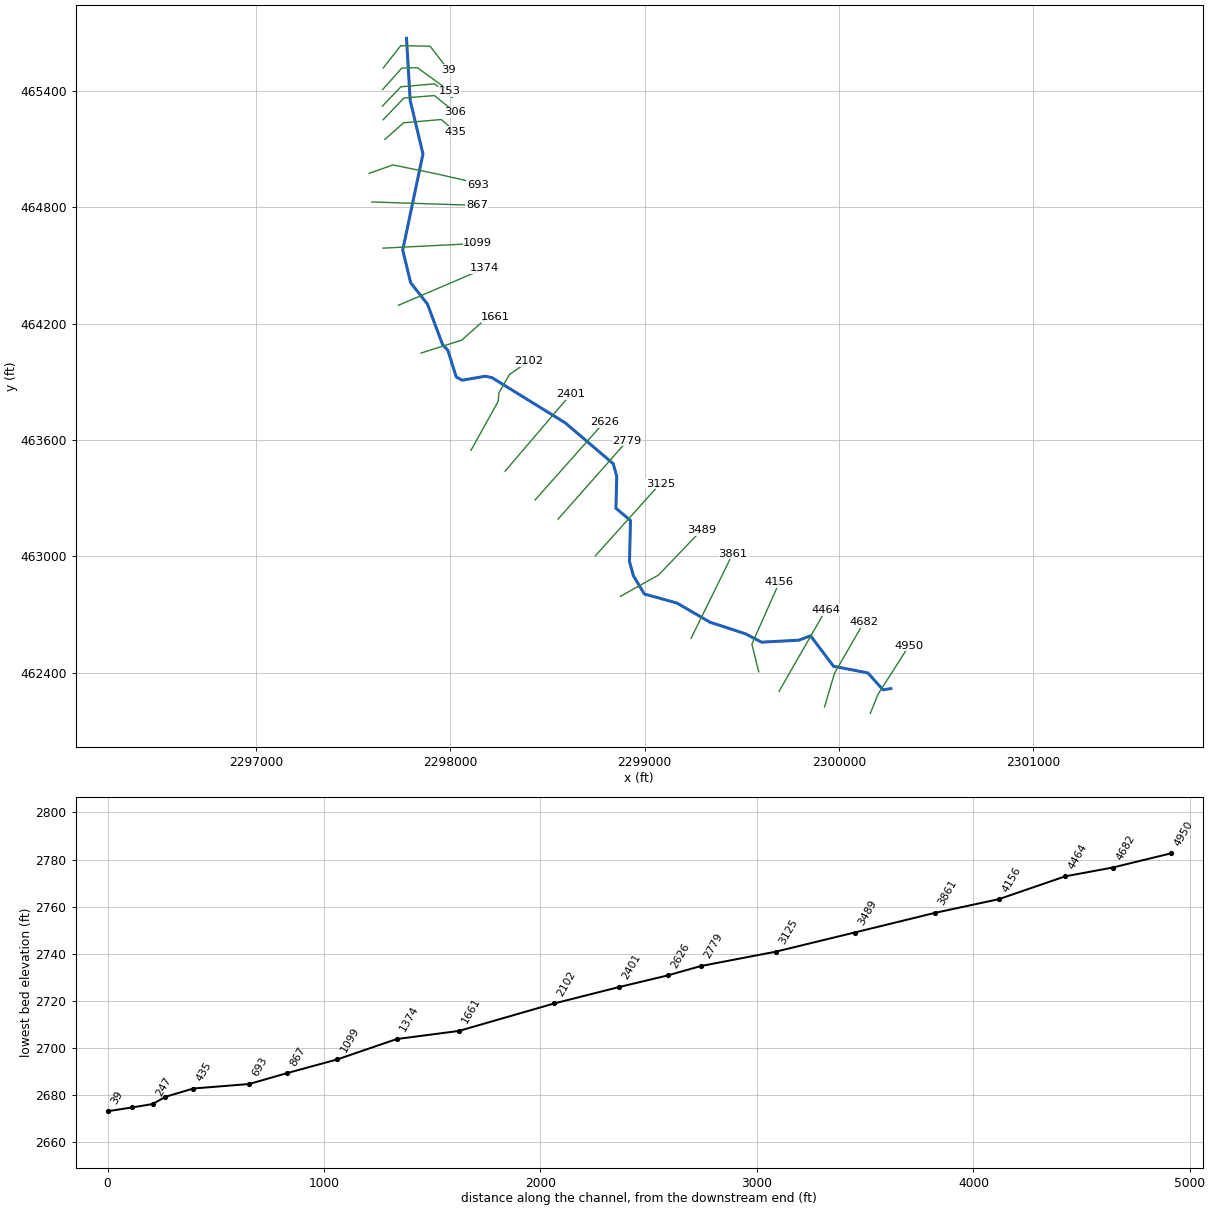
--- BIRDRN.prj (project) ---

Proj Title=BIRDRN
Current Plan=p01
Default Exp/Contr=0,0
English Units
Geom File=g01
Flow File=f01
Plan File=p01
Background Map Layer=Inundation Boundary (01pct Value_0)
BEGIN DESCRIPTION:
----------MODEL BY WOOD PLC 2021----------
Stream Name: Bird Run
Flood Zone: Enhanced Approximate
Pocahontas County, WV
HEC-RAS Version: RAS 6.1
Vertical Datum: NAVD88
Projection: NAD 1983 StatePlane West Virginia S FIPS 4702 (US Feet)
Terrain: 1-meter LIDAR (FEMA Region III 3DEP collected 2016-2018)
Land Use: 2019 NLCD
Hydrologic Method:
WV SIR2010-5033 regression equations
Model Notes:
Tie in with Knapp Creek
END DESCRIPTION:
DSS Export Rating Curves= 0
DSS Export Rating Curve Sorted= 0
DSS Export Volume Flow Curves= 0
DXF OffsetX= 0
DXF OffsetY= 0
DXF ScaleX= 0
DXF ScaleY= 0

--- BIRDRN.p01 (plan) ---

Plan Title=Floodplain
Program Version=6.10
Short Identifier=Floodplain
Geom File=g01
Flow File=f01
Subcritical Flow
K Sum by GR= 0
Std Step Tol= 0.01
Critical Tol= 0.01
Num of Std Step Trials= 20
Max Error Tol= 0.3
Flow Tol Ratio= 0.001
Split Flow NTrial= 30
Split Flow Tol= 0.02
Split Flow Ratio= 0.02
Log Output Level= 0
Friction Slope Method= 1
Unsteady Friction Slope Method= 2
Unsteady Bridges Friction Slope Method= 1
Parabolic Critical Depth
Global Vel Dist= 0 , 0 , 0
Global Log Level= 0
CheckData=True
Encroach Param=-1 ,0,0, 0
Mapping Interval=1HOUR
Computation Time Step Use Courant=        0
Computation Time Step Use Time Series=    0
Computation Time Step Count To Double=0
Computation Time Step Max Doubling=0
Computation Time Step Max Halving=0
Computation Time Step Residence Courant=0
Run HTab= 0
Run UNet= 0
Run Sediment= 0
Run PostProcess= 0
Run WQNet= 0
Run RASMapper=-1
UNET Theta= 0
UNET Theta Warmup= 0
UNET ZTol= 0
UNET ZSATol= 0
UNET MxIter= 0
UNET Max Iter WO Improvement= 0
UNET MaxInSteps= 0
UNET DtIC= 0
UNET DtMin= 0
UNET MaxCRTS= 0
UNET WFStab= 0
UNET SFStab= 0
UNET WFX= 1
UNET SFX= 1
UNET Gravity=32.174
UNET 1D Methodology=Finite Difference
UNET DSS MLevel= 1
UNET Pardiso=0
UNET DZMax Abort= 0
UNET Use Existing IB Tables= 0
UNET Froude Reduction=False
UNET Froude Limit= 0
UNET Froude Power= 0
UNET D1 Cores= 0
UNET WindReference=Eulerian
UNET WindDragFormulation=Hsu (1988)
UNET D2 Coriolis=0
UNET D2 Cores= 0
UNET D2 Theta= 1
UNET D2 Theta Warmup= 1
UNET D2 Z Tol= 0.01
UNET D2 Volume Tol= 0.01
UNET D2 Max Iterations= 20
UNET D2 Equation= 0
UNET D2 RampUpFraction=0.1
UNET D2 TimeSlices= 1
UNET D2 Turbulence Formulation=Non-Conservative (original)
UNET D2 Eddy Viscosity=0.3
UNET D2 Transverse Eddy Viscosity=0.1
UNET D2 Smagorinsky Mixing=0
UNET D2 BCVolumeCheck=0
UNET D2 Cores=0
UNET D2 SolverType=PARDISO (Direct)
UNET D2 Minimum Iterations= 2147483647
UNET D2 Maximum Iterations= 2147483647
UNET D2 Restart Number= 10
UNET D2 Relaxation Coeff=1.3
UNET D2 SOR Precondition Iterations= 10
UNET D2 ILUT Maximum Fill= 8
UNET D2 ILUT Tolerance=1E-08
UNET D1D2 MaxIter= 0
UNET D1D2 ZTol=0.01
UNET D1D2 QTol=0.1
UNET D1D2 MinQTol=1
Write IC File= 0
Write IC File at Fixed DateTime=0
Write IC File at Sim End=0
Echo Input=False
Echo Parameters=False
Echo Output=False
Write Detailed= 0
HDF Write Warmup=0
HDF Write Time Slices=0
HDF Flush=0
HDF Compression= 1
HDF Chunk Size= 1
HDF Spatial Parts= 1
HDF Use Max Rows=0
HDF Fixed Rows= 1
Calibration Method= 0
Calibration Iterations= 20
Calibration Max Change=0.05
Calibration Tolerance=0.2
Calibration Maximum=1.5
Calibration Minimum=0.5
Calibration Optimization Method= 1
WQ AD Non Conservative
WQ ULTIMATE=-1
WQ Max Comp Step=1HOUR
WQ Output Interval=15MIN
WQ Output Selected Increments= 0
WQ Output face flow=0
WQ Output face velocity=0
WQ Output face area=0
WQ Output face dispersion=0
WQ Output cell volume=0
WQ Output cell surface area=0
WQ Output cell continuity=0
WQ Output cumulative cell continuity=0
WQ Output face conc=0
WQ Output face dconc_dx=0
WQ Output face courant=0
WQ Output face peclet=0
WQ Output face adv mass=0
WQ Output face disp mass=0
WQ Output cell mass=0
WQ Output cell source sink temp=0
WQ Output nsm pathways=0
WQ Output nsm derived pathways=0
WQ Create Restart=0
WQ Fixed Restart=0
WQ System Summary=0
WQ Write To DSS=0
Sorting and Armoring Iterations= 10
XS Update Threshold= 0.02
Bed Roughness Predictor= 0
Hydraulics Update Threshold= 0.02
Energy Slope Method= 1
Volume Change Method= 1
Sediment Retention Method= 0
Sediment TS Multiplier= 1
Warm Up Method= 0
XS Weighting Method= 0
Number of US Weighted Cross Sections= 1
Number of DS Weighted Cross Sections= 1
Upstream XS Weight=0
Main XS Weight=1
Downstream XS Weight=0
Number of DS XS's Weighted with US Boundary= 1
Upstream Boundary Weight= 1
Weight of XSs Associated with US Boundary= 0
Number of US XS's Weighted with DS Boundary= 1
Downstream Boundary Weight= 0.5
Weight of XSs Associated with DS Boundary= 0.5
Percentile Method= 0
Sediment Output Level= 3
Mass or Volume Output= 0
Output Increment Type= 1
Profile and TS Output Increment= 1
Transport Output Increment 1
XS Output Flag= 0
XS Output Increment= 10
Read HDF5 Sediment Hotstart= 0
Sediment Hotstart Type= 0
Write Gradation File= 0
Read Gradation Hotstart= 0
Write HDF5 File= 1
Write Binary Output= 1
Write DSS Sediment File= 0
DSS Sediment Output Type= 1
SV Curve= 0
Specific Gage Flag= 0
Subcell Erosion Methods= 0
Subcell Deposition Methods= 0
Advection Scheme= 1
Matrix Solver= 0
Implicit Weighting Factor= 1
Maximum Outer Loop Convergence Iterations= 5
Convergence Maximum Absolute= 0.001
Convergence RMSE= 0.0001
Grain Fractions Max Abs Error= 0.001
Max Subgrid Regions= 1
Max Subgrid Length Scale= 3.402823E+38
Initial Layer Thickness= 3.402823E+38
Min Layer Thickness= 3.402823E+38
Max Layer Thickness= 3.402823E+38
Number of Layers= 5

--- BIRDRN.f01 (steady flow) ---

Flow Title=Flow
Program Version=6.10
Number of Profiles= 6
Profile Names=01pct,10pct,04pct,02pct,0_2pct,01plus
River Rch & RM=BIRDRN,Main            ,4950
     781     418     552     663    1080    1160
Boundary for River Rch & Prof#=BIRDRN,Main            , 1
Up Type= 0
Dn Type= 3
Dn Slope=0.01536
Boundary for River Rch & Prof#=BIRDRN,Main            , 2
Up Type= 0
Dn Type= 3
Dn Slope=0.01536
Boundary for River Rch & Prof#=BIRDRN,Main            , 3
Up Type= 0
Dn Type= 3
Dn Slope=0.01536
Boundary for River Rch & Prof#=BIRDRN,Main            , 4
Up Type= 0
Dn Type= 3
Dn Slope=0.01536
Boundary for River Rch & Prof#=BIRDRN,Main            , 5
Up Type= 0
Dn Type= 3
Dn Slope=0.01536
Boundary for River Rch & Prof#=BIRDRN,Main            , 6
Up Type= 0
Dn Type= 3
Dn Slope=0.01536
DSS Import GetInterval= 0
DSS Import GetPeak= 0
DSS Import FillOption= 0

--- BIRDRN.g01 (geometry) ---

Geom Title=Geometry
Program Version=6.10

River Reach=BIRDRN          ,Main
Reach XY= 30
     2300268.157      462317.441     2300227.016      462311.398
2300149.97719375462398.259311248     2299972.401      462432.739
2299854.61608671462589.844894194     2299793.158      462566.947
     2299602.194      462556.912     2299519.469       462599.91
     2299336.831      462659.851     2299165.754      462759.078
     2298998.503      462805.344      2298942.19      462899.296
     2298922.019      462973.232     2298927.264       463184.72
      2298852.14      463247.807     2298856.479      463412.377
     2298838.051      463477.897     2298591.103      463688.416
     2298214.215       463921.43     2298180.127       463928.99
2298060.40189722463908.5162974432298029.99148723463925.242022939
2297986.82844009464062.4228210242297959.63057977464091.887169712
2297881.84014476464300.8165455142297795.04181913464411.745523023
2297754.28536952464580.001003907      2297858.55      465075.985
     2297792.791        465351.7     2297773.708      465672.349

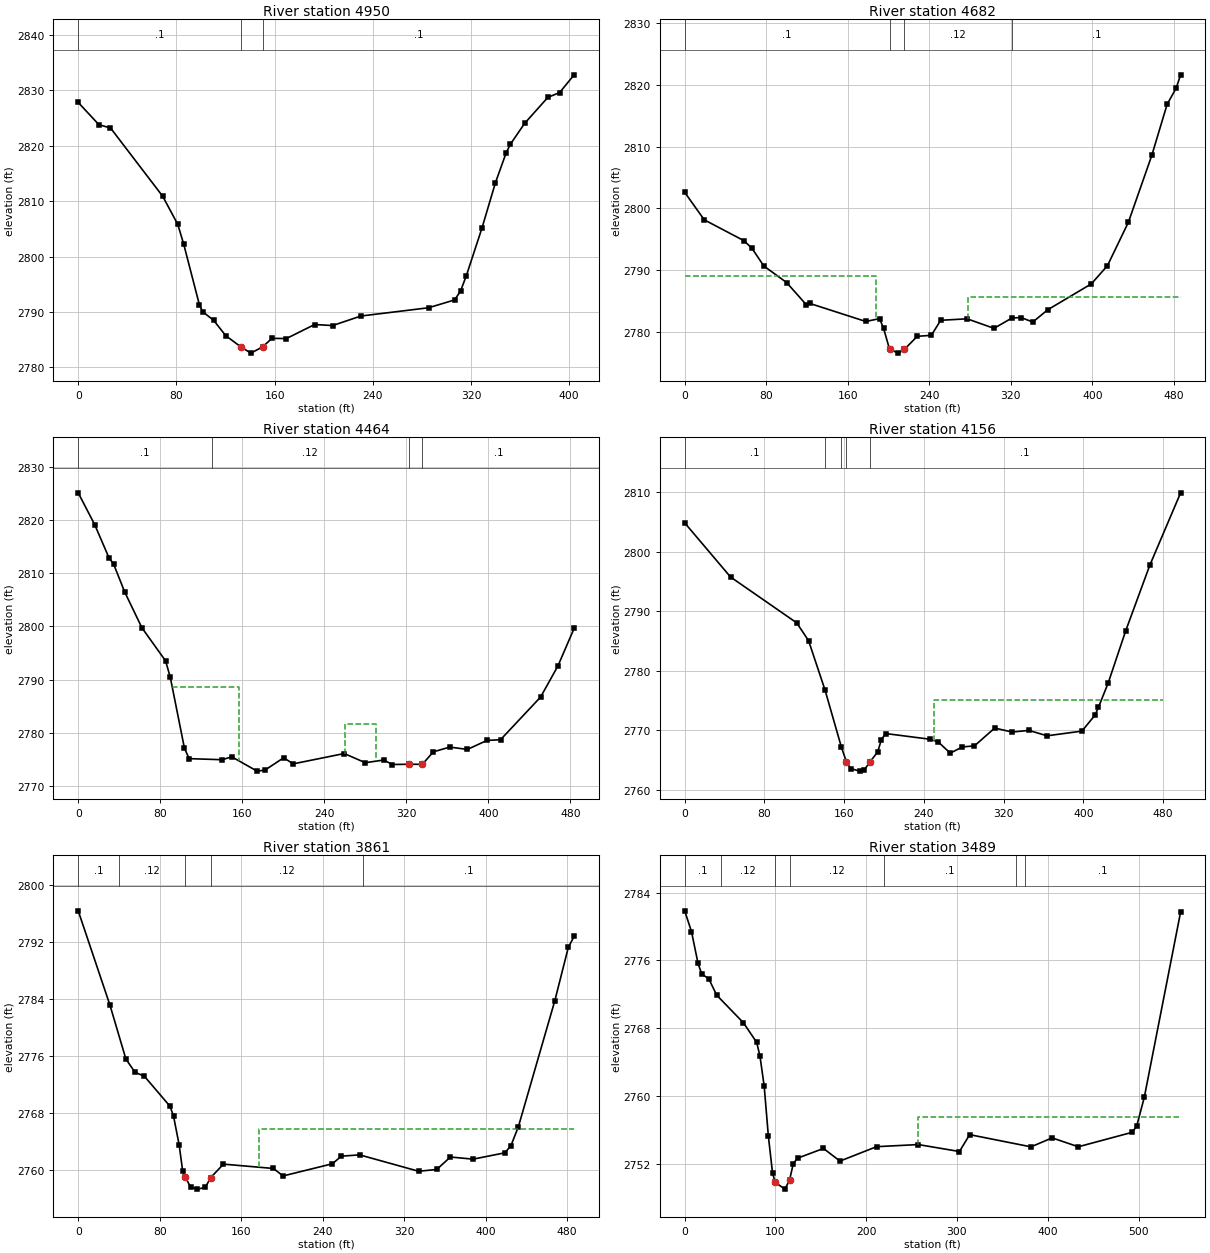
Type RM Length L Ch R = 1 ,4950    ,268,268,268
XS GIS Cut Line= 3
2300162.36928221462189.518120731 2300202.1071652462288.421296162
2300361.94176121462539.211491005
#Sta/Elev= 30
       0 2827.79    16.9 2823.77    26.3 2823.19    68.8 2810.88    81.1 2805.81
    85.9 2802.27    98.8 2791.24   101.4 2790.06   110.4 2788.49   120.2 2785.73
   132.8 2783.67   140.7 2782.59   150.2 2783.72   157.9 2785.26   169.5 2785.21
   192.6 2787.75   207.2 2787.56   230.3 2789.28   285.4 2790.77   306.7 2792.19
   311.6 2793.86   316.2 2796.57   328.8 2805.07   339.9 2813.33   348.6  2818.7
     352 2820.23   363.6    2824   382.6 2828.71   392.1 2829.56     404 2832.77
#Mann= 3 ,-1,0
       0      .1       0   132.8    .045       0   150.2      .1       0
Bank Sta=132.8,150.2
XS Rating Curve= 0 ,0
Exp/Cntr(USF)=0,0
Exp/Cntr=0.3,0.1

Type RM Length L Ch R = 1 ,4682    ,219.6,218.9,219.3
XS GIS Cut Line= 3
2299926.37832167462222.763078824 2299977.6556204462396.227433474
2300130.34023246462661.121176696
#Sta/Elev= 30
       0  2802.6    19.2 2798.15    58.1 2794.78    66.1 2793.53    77.6 2790.69
     100 2788.01   119.2 2784.44   122.5 2784.64   177.7 2781.71   191.2 2782.17
   195.1 2780.63     201 2777.22   209.7 2776.59   215.6  2777.2   228.2 2779.31
     242 2779.47   251.2  2781.9   277.1 2782.14   303.5  2780.6   321.1 2782.27
   329.9 2782.35   341.6 2781.62   356.2  2783.6     399 2787.79   414.8 2790.73
   435.3 2797.74   458.3 2808.56   473.4 2816.85   482.2 2819.43   486.6  2821.6
#Mann= 4 ,-1,0
       0      .1       0     201    .045       0   215.6     .12       0
   321.1      .1       0
#XS Ineff= 2 , 0
          187.72 2789.07  277.59         2785.74
Permanent Ineff=
       F       F
Bank Sta=201,215.6
XS Rating Curve= 0 ,0
Exp/Cntr(USF)=0,0
Exp/Cntr=0.3,0.1

Type RM Length L Ch R = 1 ,4464    ,308.2,307.3,306.6
XS GIS Cut Line= 2
2299692.13934139462303.2528840042299932.44453923462722.948706292
#Sta/Elev= 30
       0 2825.07    16.1 2819.09    29.9 2812.93    34.5 2811.71    45.4 2806.44
    62.1 2799.76    85.2 2793.55    89.8 2790.46   103.6 2777.15   108.2 2775.21
   140.5 2775.01   149.7 2775.56   174.4 2772.87     182 2773.05   200.4 2775.38
   209.6 2774.23   259.4 2776.17   279.9 2774.45   297.9 2774.95   306.4 2774.11
   322.1 2774.16   335.6 2774.15   346.2 2776.48   362.3 2777.38   379.5 2776.94
   398.6 2778.63   411.8 2778.76   450.9 2786.77   467.8 2792.61   483.6 2799.67
#Mann= 4 ,-1,0
       0      .1       0     130     .12       0   322.1    .045       0
   335.6      .1       0
#XS Ineff= 2 ,-1
   91.36  156.992788.581  259.97   290.7 2781.71
Permanent Ineff=
       F       F
Bank Sta=322.1,335.6
XS Rating Curve= 0 ,0
Exp/Cntr(USF)=0,0
Exp/Cntr=0.3,0.1

Type RM Length L Ch R = 1 ,4156    ,295.6,295.1,294.2
XS GIS Cut Line= 3
2299587.41773312462404.4823776692299552.42701706462546.911177636
2299694.49038134462867.655849639
#Sta/Elev= 30
       0 2804.84      46 2795.75   112.4 2788.05   124.3 2785.05   140.8 2776.77
   157.3 2767.14   162.3  2764.7   166.6 2763.59   175.4 2763.16   179.8 2763.29
   185.6 2764.64   193.7 2766.41   197.3 2768.45   201.6 2769.47   245.8 2768.52
   254.3 2768.07   266.4 2766.18   278.6 2767.22   290.7  2767.4     311 2770.39
   328.5 2769.72   345.3    2770   363.5 2769.09   398.5 2769.88   411.6 2772.55
     415 2773.85   424.8 2777.94   442.3 2786.66   466.5 2797.69   497.5 2809.88
#Mann= 5 ,-1,0
       0      .1       0   140.8     .12       0   157.3      .1       0
   162.3    .045       0   185.6      .1       0
#XS Ineff= 1 ,-1
     250 479.917 2775.13
Permanent Ineff=
       F
Bank Sta=162.3,185.6
XS Rating Curve= 0 ,0
Exp/Cntr(USF)=0,0
Exp/Cntr=0.3,0.1

Type RM Length L Ch R = 1 ,3861    ,379.4,371.6,364.6
XS GIS Cut Line= 2
2299239.56733288462577.183245858  2299454.151901  463014.2999587
#Sta/Elev= 30
       0 2796.42    31.2 2783.16    46.8 2775.61    55.8 2773.74    64.9  2773.2
    90.1 2768.98    93.6 2767.58    99.1 2763.55   102.5 2759.94   105.1 2759.04
   110.3 2757.63     117 2757.34   124.8 2757.58     130 2758.95   142.6 2760.85
   191.7 2760.24   201.1 2759.19   249.5  2760.9   258.4 2761.97   276.3 2762.15
   334.2 2759.85     352  2760.1   365.4 2761.85   387.7 2761.55   418.9 2762.44
   424.9 2763.46   432.2 2766.13   467.9 2783.79   481.2  2791.3   486.9 2792.84
#Mann= 5 ,-1,0
       0      .1       0      40     .12       0   105.1    .045       0
     130     .12       0     280      .1       0
#XS Ineff= 2 , 0
                          177.74         2765.85
Permanent Ineff=
       F       F
Bank Sta=105.1,130
XS Rating Curve= 0 ,0
Exp/Cntr(USF)=0,0
Exp/Cntr=0.3,0.1

Type RM Length L Ch R = 1 ,3489    ,360.7,364.6,372.2
XS GIS Cut Line= 3
2298875.74493754462793.5339421132299071.84936736462903.430917703
2299294.03742326463135.946428948
#Sta/Elev= 30
       0 2781.84     7.5 2779.39    14.7 2775.64    18.8 2774.37    26.5 2773.83
    35.3 2771.88    64.7 2768.63    79.4  2766.3      83 2764.65    87.6 2761.14
    92.2 2755.25    96.8 2750.8899.798342749.779   110.5 2748.99115.49812750.053
   119.7    2752   124.3 2752.64   152.9 2753.79   171.1  2752.3   211.4    2754
   257.4 2754.25   302.7 2753.43     314 2755.42   381.6 2753.98   404.8 2755.04
   433.7 2753.99   492.8 2755.69   497.9 2756.39   506.4 2759.84   546.4 2781.71
#Mann= 7 ,-1,0
       0      .1       0      40     .12       099.79834    .045       0
115.4981     .12       0     220      .1       0   364.8     .12       0
   374.8      .1       0
#XS Ineff= 2 , 0
                           256.9         2757.53
Permanent Ineff=
       F       F
Bank Sta=99.79834,115.4981
XS Rating Curve= 0 ,0
Exp/Cntr(USF)=0,0
Exp/Cntr=0.3,0.1

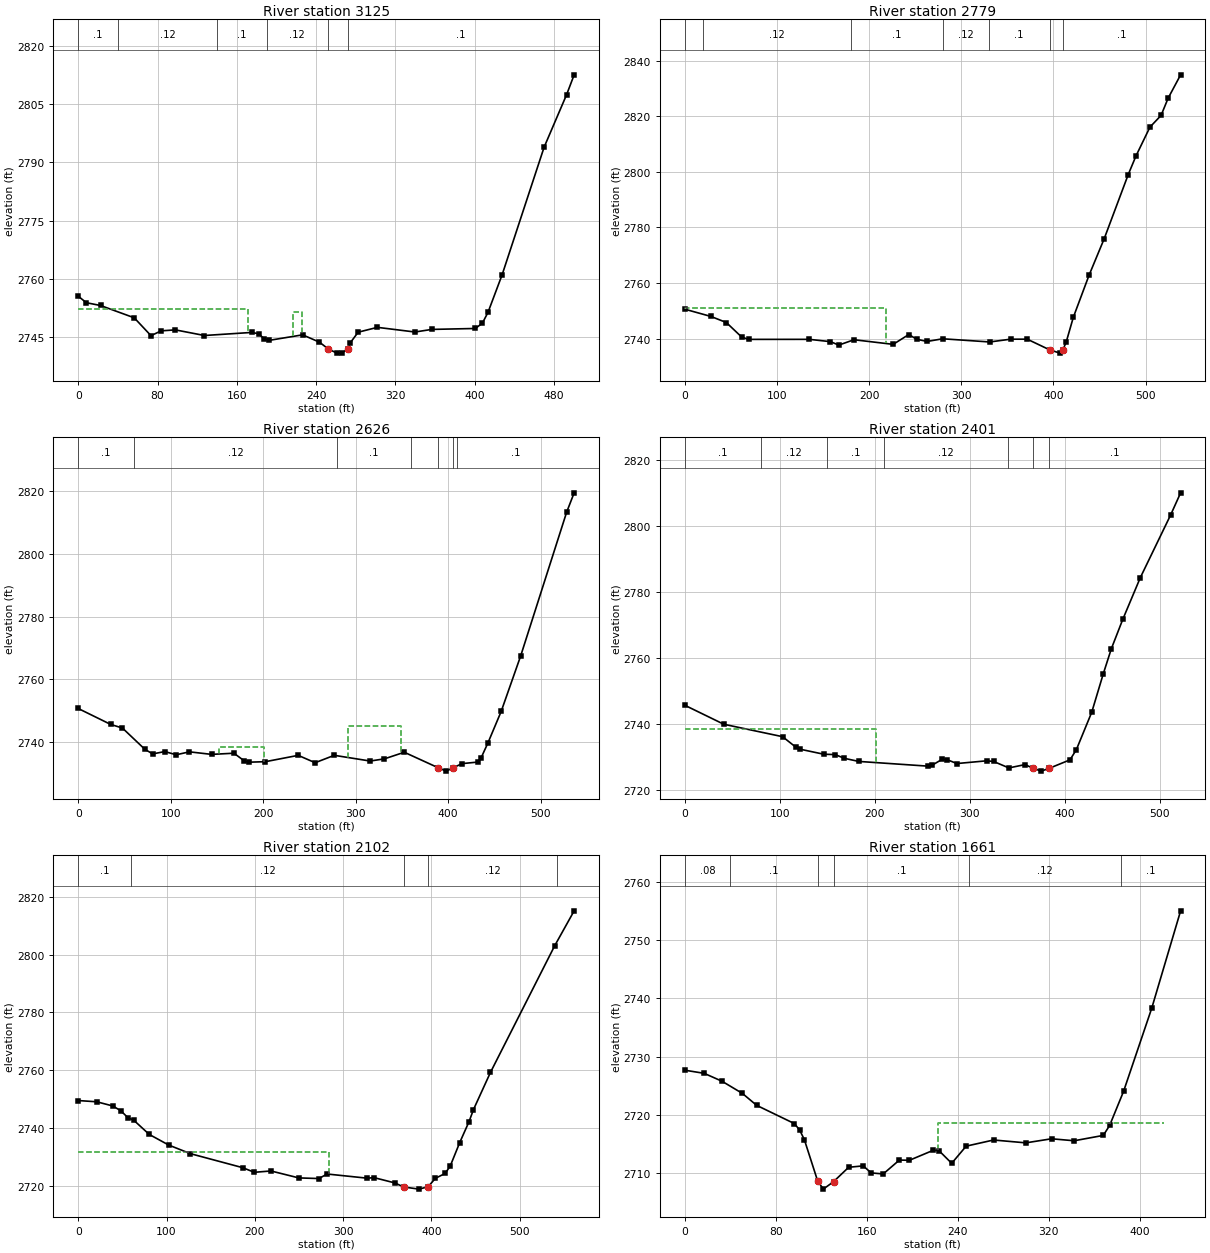
Type RM Length L Ch R = 1 ,3125    ,344.7,345.6,341
XS GIS Cut Line= 2
2298746.81758385463002.8201258382299080.61580093463375.473161837
#Sta/Elev= 30
       0 2755.51     8.3 2753.83    22.5 2753.12    56.5 2749.95    73.4 2745.35
    83.7 2746.59      98 2746.84   127.3 2745.39     175 2746.18   181.9 2745.85
   187.9 2744.47   192.4 2744.13   226.4 2745.56   243.4 2743.67   251.9 2741.99
   260.9 2740.85   266.1 2740.87   271.8 2741.94   274.6 2743.56   282.4 2746.24
   301.8 2747.49   339.7 2746.29   356.7 2746.96   400.6  2747.2   407.7 2748.56
   413.4 2751.36   427.7 2761.08     470  2793.9   492.7 2807.44   500.3 2812.54
#Mann= 6 ,-1,0
       0      .1       0      40     .12       0     140      .1       0
     190     .12       0   251.9    .045       0   271.8      .1       0
#XS Ineff= 2 ,-1
       0  171.38 2752.14  216.28  225.252751.516
Permanent Ineff=
       F       F
Bank Sta=251.9,271.8
XS Rating Curve= 0 ,0
Exp/Cntr(USF)=0,0
Exp/Cntr=0.3,0.1

Type RM Length L Ch R = 1 ,2779    ,153.9,153.7,153.8
XS GIS Cut Line= 2
2298554.30961739463191.7958360372298910.18443613463595.356114358
#Sta/Elev= 30
       0 2750.59    28.5 2747.96    45.2 2745.78    61.8 2740.56    69.3 2739.71
   135.2 2739.72   158.2 2738.89   167.2 2737.65   183.7 2739.58   226.2 2737.92
   243.2 2741.46   251.7 2739.75     263 2738.97     280 2739.92     331 2738.78
   353.6 2739.78   371.7 2739.78   395.9 2735.96   407.2 2734.76   410.4 2735.92
   414.1 2738.91   421.7 2747.67   438.7 2762.76   455.2 2775.96   481.2 2798.99
   489.7 2805.76   504.8 2816.11   516.9 2820.34   524.5  2826.5   538.1 2834.94
#Mann= 7 ,-1,0
       0      .1       0      20     .12       0     180      .1       0
     280     .12       0     330      .1       0   395.9    .045       0
   410.4      .1       0
#XS Ineff= 2 , 0
          218.27 2751.02
Permanent Ineff=
       F       F
Bank Sta=395.9,410.4
XS Rating Curve= 0 ,0
Exp/Cntr(USF)=0,0
Exp/Cntr=0.3,0.1

Type RM Length L Ch R = 1 ,2626    ,223.8,224.5,224.3
XS GIS Cut Line= 2
2298436.47862988463291.1688299682298792.33111814463692.449295452
#Sta/Elev= 30
       0 2750.73    35.2 2745.64    47.8  2744.5      72 2737.74    80.5 2736.25
    93.6 2736.99     106 2735.98   120.3 2736.91   144.2  2736.1   168.4 2736.47
   179.7    2734   184.5 2733.61   202.4 2733.77   237.9 2735.79   256.2 2733.44
   276.9  2735.8   315.7 2733.98   331.1 2734.67   352.6 2736.78   389.4 2731.82
   397.9 2730.76   405.1 2731.76   414.9 2733.15   431.9 2733.64   435.7    2735
   443.2 2739.85   457.4 2749.81   478.5 2767.52   528.2 2813.34   536.3 2819.49
#Mann= 7 ,-1,0
       0      .1       0      60     .12       0     280      .1       0
     360     .12       0   389.4    .045       0   405.1     .12       0
     410      .1       0
#XS Ineff= 2 ,-1
  152.44  200.57 2738.43  292.03  348.84 2745.12
Permanent Ineff=
       F       F
Bank Sta=389.4,405.1
XS Rating Curve= 0 ,0
Exp/Cntr(USF)=0,0
Exp/Cntr=0.3,0.1

Type RM Length L Ch R = 1 ,2401    ,296.8,299.4,301.9
XS GIS Cut Line= 2
2298281.44282089463439.053774614 2298619.6563583463836.432604471
#Sta/Elev= 30
       0  2745.8    41.2 2740.02     103 2736.26   116.9 2733.09   121.5 2732.46
   146.2 2730.95   158.5 2730.82     168  2729.7   183.2 2728.76     256 2727.33
   260.2 2727.59   270.7 2729.37   275.8 2729.32   286.4 2728.12   317.9 2728.95
   325.1 2728.74   341.1 2726.79   358.1  2727.8   366.7 2726.68   375.2 2725.82
   383.7 2726.69   405.4 2729.24   412.1 2732.32   428.3 2743.68   440.4 2755.29
   448.9  2762.9   460.9 2771.78   479.4 2784.46   511.4 2803.52   521.8 2810.16
#Mann= 7 ,-1,0
       0      .1       0      80     .12       0     150      .1       0
     210     .12       0     340      .1       0   366.7    .045       0
   383.7      .1       0
#XS Ineff= 2 , 0
          200.79 2738.45
Permanent Ineff=
       F       F
Bank Sta=366.7,383.7
XS Rating Curve= 0 ,0
Exp/Cntr(USF)=0,0
Exp/Cntr=0.3,0.1

Type RM Length L Ch R = 1 ,2102    ,446.7,440.6,428.3
XS GIS Cut Line= 5
2298105.71307168463546.7875907092298246.08965555463799.764440149
2298249.44275133463842.7958360422298304.20998247463938.359065884
2298402.57628178464005.289739967
#Sta/Elev= 30
       0 2749.51      21 2749.08    39.3 2747.62    48.5 2745.91    56.5 2743.51
    62.8 2742.73    80.5 2737.78   102.6  2734.1   127.1 2731.13   186.4 2726.28
   199.4 2724.69   218.3 2725.15   249.8 2722.75   272.6 2722.53   281.8  2724.1
   326.8 2722.67   335.2 2722.83   358.3 2721.04   368.5 2719.62   385.9 2718.87
   396.3  2719.7   404.4  2722.6   415.4 2724.28   421.2  2726.8     432 2734.96
   442.6 2742.24   447.6 2746.39   466.8 2759.23   539.6 2803.07   561.6 2815.13
#Mann= 5 ,-1,0
       0      .1       0      60     .12       0   368.5    .045       0
   396.3     .12       0  542.62      .1       0
#XS Ineff= 2 , 0
          284.28 2731.83
Permanent Ineff=
       F       F
Bank Sta=368.5,396.3
XS Rating Curve= 0 ,0
Exp/Cntr(USF)=0,0
Exp/Cntr=0.3,0.1

Type RM Length L Ch R = 1 ,1661    ,285.6,286.7,287.9
XS GIS Cut Line= 4
2297847.85836431464048.3679803952298057.68740945464114.973739955
2298172.36328526464217.0755065752298232.79745534464232.755784878
#Sta/Elev= 30
       0 2727.66    17.1 2727.12    32.8 2725.76    50.7 2723.67    63.3 2721.61
    96.5 2718.47   101.1 2717.36   105.2 2715.73116.84372708.653   121.9  2707.2
130.89292708.481   144.2 2710.96     157  2711.2     164 2709.99   174.6 2709.81
   188.8  2712.2   197.6 2712.16   218.6 2713.88   223.5 2713.84   234.8 2711.64
   247.5 2714.59   271.6 2715.65     300 2715.16   322.6 2715.86   342.5 2715.52
   368.1 2716.44   373.7 2718.16   385.9    2724   410.7 2738.32   436.1 2755.07
#Mann= 6 ,-1,0
       0     .08       0      40      .1       0116.8437    .045       0
130.8929      .1       0  250.15     .12       0  383.69      .1       0
#XS Ineff= 1 ,-1
  222.82421.1114 2718.54
Permanent Ineff=
       F
Bank Sta=116.8437,130.8929
XS Rating Curve= 0 ,0
Exp/Cntr(USF)=0,0
Exp/Cntr=0.3,0.1

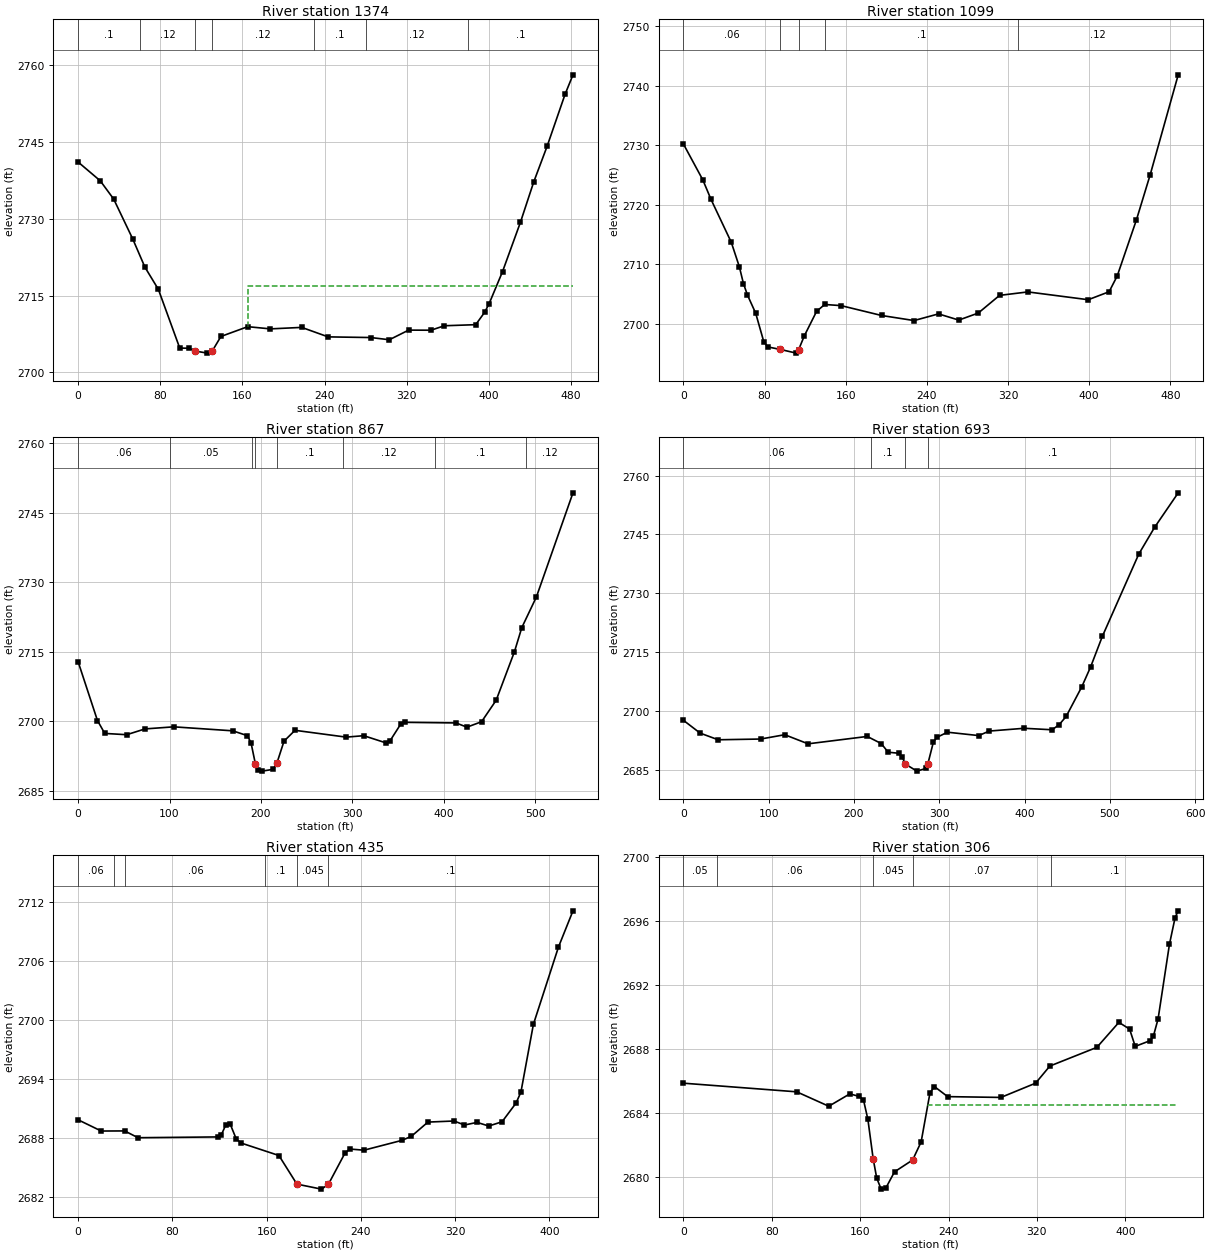
Type RM Length L Ch R = 1 ,1374    ,279,275.5,269.7
XS GIS Cut Line= 2
 2297732.4180006464295.1169020562298175.22866639464484.892901683
#Sta/Elev= 30
       0 2741.03    21.5 2737.38    34.6 2733.81    53.2 2726.01      65 2720.53
    78.1  2716.2    98.9 2704.75     108 2704.71   114.1 2704.16   125.9 2703.76
   130.3 2704.08     139 2707.01   165.1 2708.92   187.2 2708.49   217.7 2708.78
   243.4 2706.93     285  2706.8     303 2706.37   321.8 2708.25   343.5 2708.23
   356.6  2709.1   387.1 2709.31   395.8 2711.73   400.1 2713.38   413.2 2719.66
   430.6 2729.26   443.6 2737.16   456.7 2744.16   474.1 2754.25   481.8 2758.05
#Mann= 7 ,-1,0
       0      .1       0      60     .12       0   114.1    .045       0
   130.3     .12       0     230      .1       0     280     .12       0
     380      .1       0
#XS Ineff= 1 ,-1
  165.07481.7636 2716.83
Permanent Ineff=
       F
Bank Sta=114.1,130.3
XS Rating Curve= 0 ,0
Exp/Cntr(USF)=0,0
Exp/Cntr=0.3,0.1

Type RM Length L Ch R = 1 ,1099    ,231.4,231.8,230
XS GIS Cut Line= 2
2297653.00818515464589.8753695612298140.23451043464614.102092918
#Sta/Elev= 30
       0 2730.22    19.2 2724.17    27.2 2720.92    47.2 2713.71    55.2 2709.58
    59.2 2706.77    63.2 2704.83    71.3 2701.78    79.3 2696.98    83.3 2696.13
    95.3 2695.72   111.3 2695.09   113.6 2695.67   119.3 2698.02   131.3  2702.1
   139.3 2703.26   155.4 2703.07   195.4 2701.41   227.4 2700.56   251.5 2701.68
   271.5 2700.64   290.7 2701.82   311.7 2704.79   339.6 2705.37   399.1 2704.06
   419.7  2705.4   427.7 2708.06   446.6 2717.46   460.2 2725.06   487.8 2741.83
#Mann= 5 ,-1,0
       0     .06       0    95.3    .045       0   113.6     .06       0
     140      .1       0     330     .12       0
Bank Sta=95.3,113.6
XS Rating Curve= 0 ,0
Exp/Cntr(USF)=0,0
Exp/Cntr=0.3,0.1

Type RM Length L Ch R = 1 ,867     ,177.3,174.2,171.8
XS GIS Cut Line= 2
2297595.13323491464828.1048159012298136.19672321464810.607737922
#Sta/Elev= 30
       0 2712.84    21.1 2700.19    29.1 2697.41    53.1 2697.13    73.1 2698.38
   104.6 2698.83   169.1 2697.97   185.1 2696.93   189.1 2695.39   193.8 2690.92
   197.1 2689.49   201.1 2689.28   213.2 2689.66   217.3 2690.94   225.2 2695.74
   237.2 2698.08   293.2 2696.61   312.4 2696.92   337.2 2695.34   341.2 2695.82
   353.2 2699.52   357.2  2699.8   413.3 2699.67   425.3 2698.76   441.3 2699.93
   457.3 2704.57   477.3 2715.04   485.3 2720.21   501.3 2726.84   541.3 2749.28
#Mann= 8 ,-1,0
       0     .06       0     100     .05       0     190      .1       0
   193.8    .045       0   217.3      .1       0     290     .12       0
     390      .1       0     490     .12       0
Bank Sta=193.8,217.3
XS Rating Curve= 0 ,0
Exp/Cntr(USF)=0,0
Exp/Cntr=0.3,0.1

Type RM Length L Ch R = 1 ,693     ,252.1,257.6,262.4
XS GIS Cut Line= 5
2297581.67394416464976.1570141922297704.15349002465019.226744603
2297942.78881473464970.038259103 2298098.5107091464934.433212855
2298141.58043951  464915.5902058
#Sta/Elev= 30
       0 2697.63    19.6 2694.36    40.8 2692.66    90.6 2692.85   118.8 2693.95
   146.2 2691.63   215.6 2693.51     232 2691.69   240.1 2689.49   252.4 2689.23
   256.5 2688.29   260.3 2686.46   273.8 2684.67     285  2685.4   286.7 2686.56
   293.2 2692.12   297.3 2693.28   309.6 2694.59   346.3 2693.73   358.6 2694.88
   399.5 2695.59   432.4 2695.21   440.6 2696.51   448.8  2698.6   467.1 2706.14
   477.5 2711.23   491.2 2718.99     534    2740   552.5  2746.8   580.2  2755.6
#Mann= 4 ,-1,0
       0     .06       0  219.83      .1       0   260.3    .045       0
   286.7      .1       0
Bank Sta=260.3,286.7
XS Rating Curve= 0 ,0
Exp/Cntr(USF)=0,0
Exp/Cntr=0.3,0.1

Type RM Length L Ch R = 1 ,435     ,130.4,129.2,128.4
BEGIN DESCRIPTION:
structure xs 4
END DESCRIPTION:
XS GIS Cut Line= 4
 2297662.6988745465150.9932010832297758.93280338465236.863476091
2297953.15036896465253.4184037182298025.42676031465190.025144268
#Sta/Elev= 30
       0 2689.81    19.6 2688.67    39.5 2688.68    50.8 2687.99   118.7 2688.07
   121.6  2688.3   125.3 2689.29     129 2689.39   134.2 2687.86   138.3 2687.45
   170.4 2686.18185.6657 2683.27   206.5 2682.76  212.312683.232   226.5 2686.43
   230.6 2686.84   242.6 2686.72   274.8 2687.72   282.8 2688.13   296.9 2689.58
   319.1 2689.69   327.9 2689.28   338.6 2689.55   348.5 2689.18   359.8 2689.61
   371.6  2691.5   375.8 2692.62   386.4 2699.52   407.7 2707.39     420 2711.07
#Mann= 6 ,-1,0
       0     .06       0      30     .05       0      40     .06       0
  158.98      .1       0185.6657    .045       0  212.31      .1       0
Bank Sta=185.6657,212.31
XS Rating Curve= 0 ,0
Exp/Cntr(USF)=0,0
Exp/Cntr=0.5,0.3

Type RM Length L Ch R = 1 ,306     ,59.4,59.3,60
BEGIN DESCRIPTION:
structure xs 3; 14.4 ft between structure and xs
END DESCRIPTION:
XS GIS Cut Line= 4
2297653.27947061465252.2795862092297760.68251118465364.707343413
 2297917.3507552465377.0472114962298022.33112343465291.757987528
#Sta/Elev= 30
       0 2685.87   102.6 2685.33   131.6 2684.43   150.6  2685.2     159 2685.05
     163 2684.83     167 2683.61   171.8 2681.14     175 2679.94     179 2679.25
   183.1  2679.3   191.1 2680.33   207.5 2681.07   215.2  2682.2   223.2 2685.26
   227.2 2685.66   239.2 2685.03   287.4 2684.98   318.8 2685.87   331.7 2686.94
   374.3 2688.11   394.2 2689.67   403.9 2689.25     409 2688.17   422.6 2688.53
   425.4  2688.8   429.7 2689.89     440 2694.56   445.1 2696.22   447.9 2696.64
#Mann= 5 ,-1,0
       0     .05       0      30     .06       0   171.8    .045       0
   207.5     .07       0  332.64      .1       0
#XS Ineff= 2 , 0
             157  2683.9     221          2684.5
Permanent Ineff=
       F       F
Bank Sta=171.8,207.5
XS Rating Curve= 0 ,0
Exp/Cntr(USF)=0,0
Exp/Cntr=0.5,0.3

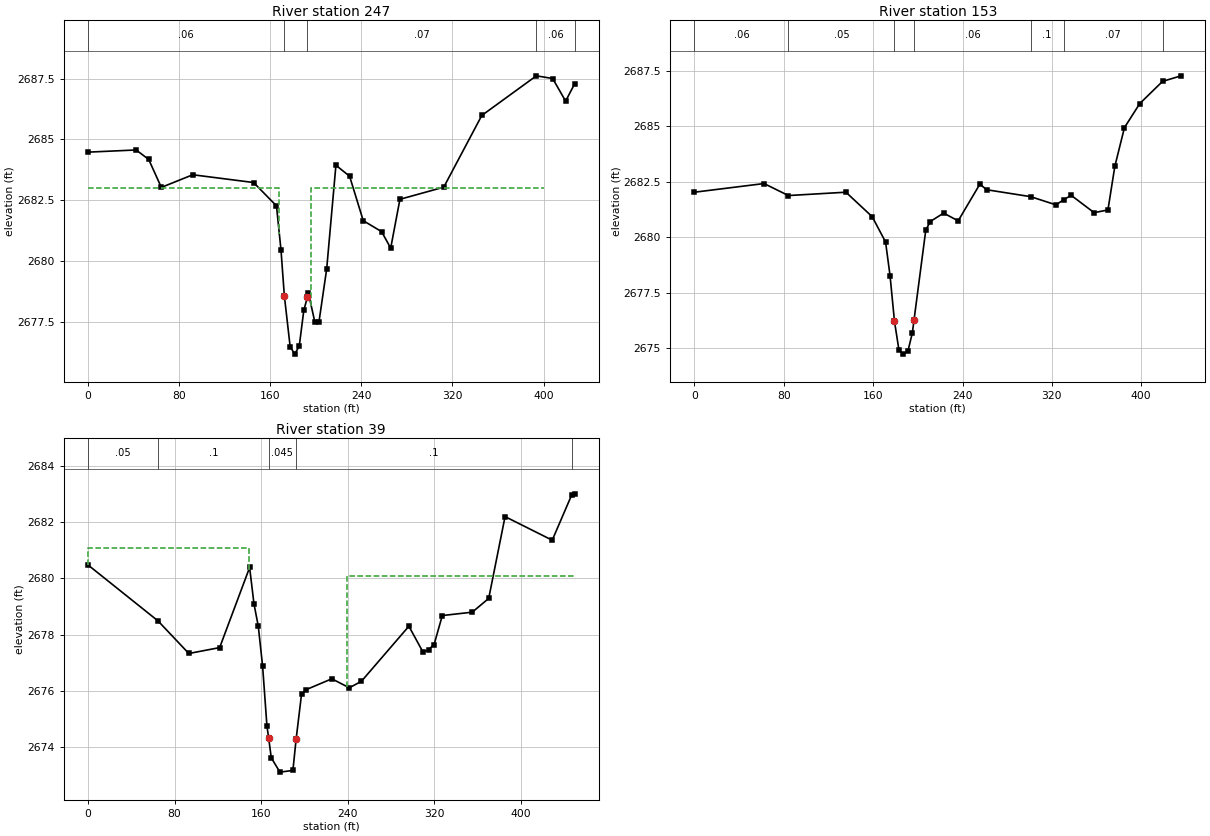
Type RM Length L Ch R = 1 ,247     ,94.6,93.6,92.9
BEGIN DESCRIPTION:
structure xs 2; 13.9 ft between structure and xs
END DESCRIPTION:
XS GIS Cut Line= 4
2297649.64546211465322.5370839432297744.53136228465422.332502676
2297918.56209137465437.6140198882298009.41230396465367.356522153
#Sta/Elev= 30
       0 2684.47    42.3 2684.56    53.3 2684.17    64.4 2683.02      92 2683.54
   145.4 2683.22   165.5 2682.26   169.5 2680.43  172.39 2678.57   177.5 2676.47
   181.5 2676.16   185.5 2676.49   189.5 2677.96  192.662678.502   193.6 2678.66
   199.1  2677.5   202.8 2677.48   209.6 2679.67   217.7 2683.93   229.7 2683.48
   241.7 2681.65   257.8  2681.2   265.8 2680.52   273.9 2682.53   312.4 2683.03
   345.8 2685.98   393.7 2687.61     408  2687.5   419.4 2686.57   427.3 2687.28
#Mann= 5 ,-1,0
       0     .06       0  172.39    .045       0  192.66     .07       0
   393.7     .06       0   427.3      .1       0
#XS Ineff= 2 ,-1
       0     168    2683     196     400    2683
Permanent Ineff=
       F       F
Bank Sta=172.39,192.66
XS Rating Curve= 0 ,0
Exp/Cntr(USF)=0,0
Exp/Cntr=0.5,0.3

Type RM Length L Ch R = 1 ,153     ,94.8,114.6,94.8
BEGIN DESCRIPTION:
structure xs 1
END DESCRIPTION:
XS GIS Cut Line= 4
2297650.77374418465407.8440419682297749.13122051465518.496202837
2297829.04667003465521.2904493232297997.26030852465399.461302508
#Sta/Elev= 30
       0 2682.03    62.3 2682.42    84.1 2681.88   135.6 2682.03   159.1 2680.93
   171.1 2679.79   175.1 2678.28   179.1 2676.21   183.1 2674.92   187.1 2674.74
   191.1 2674.87   195.1  2675.7   196.62676.283   207.1 2680.32   211.1 2680.71
   223.1 2681.09   236.1 2680.74   255.5 2682.39   261.8 2682.14     301 2681.83
   323.7 2681.46   330.5 2681.69   337.3 2681.89   357.8 2681.11   370.2 2681.23
   376.4  2683.2     385 2684.94   398.7 2686.02   419.1 2687.02   435.7 2687.27
#Mann= 7 ,-1,0
       0     .06       0    84.1     .05       0   179.1    .045       0
   196.6     .06       0     301      .1       0   330.5     .07       0
   419.1     .06       0
Bank Sta=179.1,196.6
XS Rating Curve= 0 ,0
Exp/Cntr(USF)=0,0
Exp/Cntr=0.3,0.1

Type RM Length L Ch R = 1 ,39      ,,,
XS GIS Cut Line= 4
2297654.49080678  465519.98487932297744.12758355465634.450924954
2297895.27541872465631.624473896 2297988.8195891465510.294189958
#Sta/Elev= 30
       0 2680.48    64.7 2678.49    93.2 2677.33   121.7 2677.54   149.4 2680.39
   153.4  2679.1   157.4  2678.3   161.4 2676.88   165.4 2674.75167.02942674.315
   169.4 2673.62   177.4 2673.11   189.4 2673.17  192.372674.281   197.4 2675.89
   201.4 2676.04   225.4 2676.43   241.5 2676.11   252.7 2676.34   296.6  2678.3
   309.8 2677.37   314.8 2677.47   319.9 2677.65   327.5 2678.68   355.2  2678.8
   370.4 2679.29   385.5  2682.2   429.1 2681.36   447.2 2682.98   449.8 2683.01
#Mann= 5 ,-1,0
       0     .05       0    64.7      .1       0167.0294    .045       0
  192.37      .1       0   447.2     .06       0
#XS Ineff= 2 , 0
          148.67  2681.1   239.2         2680.08
Permanent Ineff=
       F       F
Bank Sta=167.0294,192.37
XS Rating Curve= 0 ,0
Exp/Cntr(USF)=0,0
Exp/Cntr=0.3,0.1
LCMann Table=0

Chan Stop Cuts=-1
Use User Specified Reach Order=0
Composite Channel Slope=5